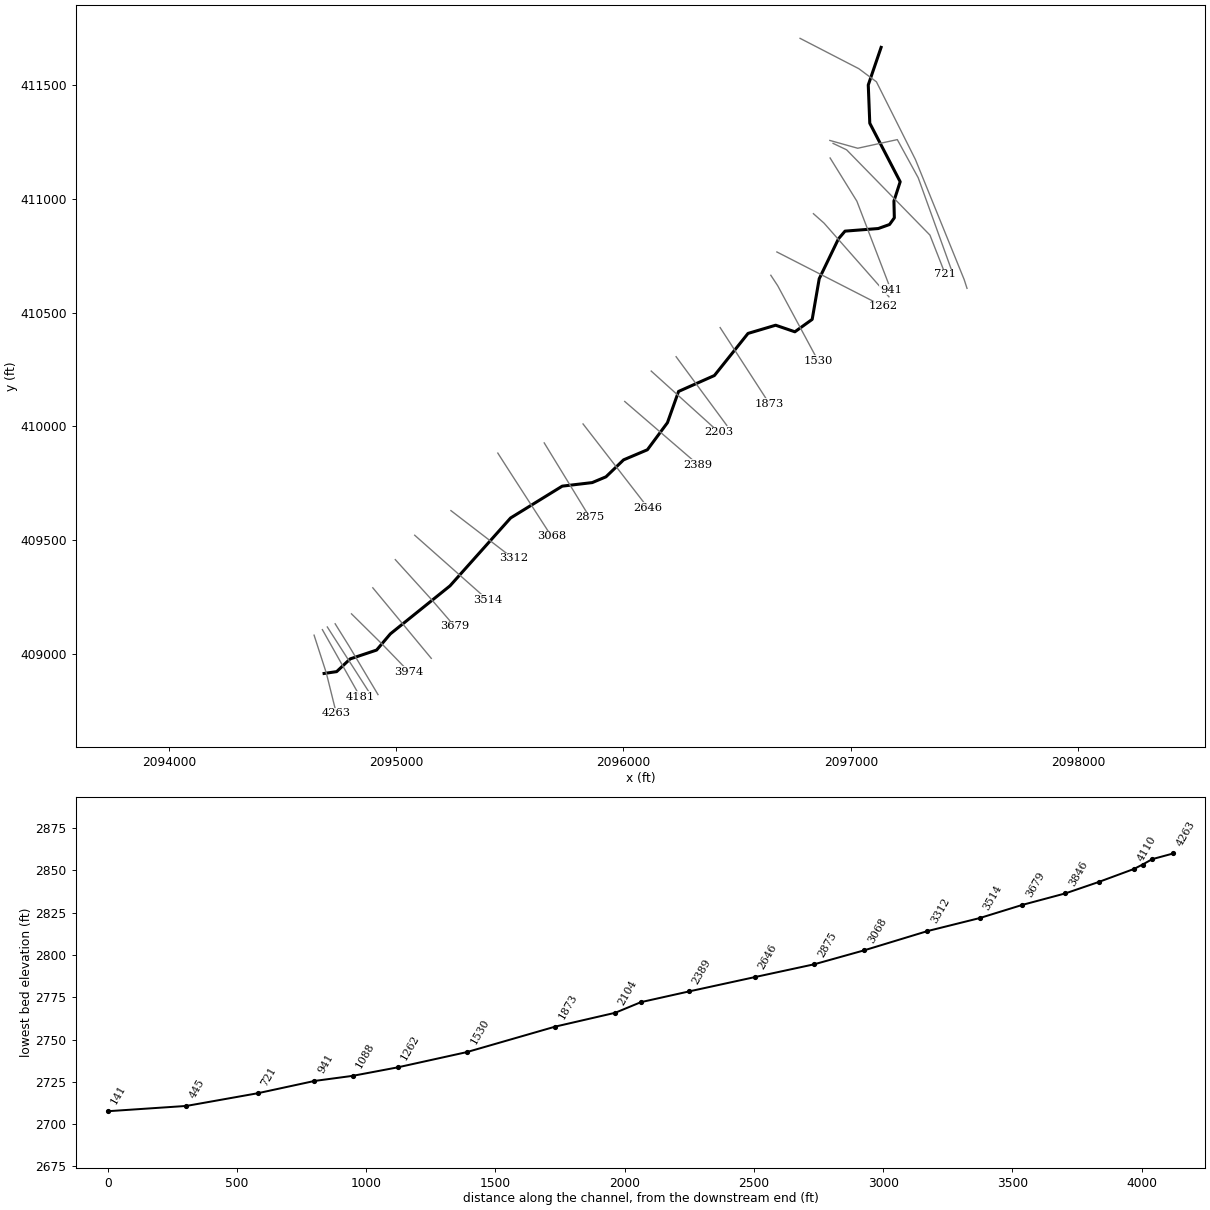
--- HOGCMPRN.prj (project) ---

Proj Title=HOGCMPRN
Current Plan=p01
Default Exp/Contr=0.3,0.1
English Units
Geom File=g01
Flow File=f01
Plan File=p01
Y Axis Title=Elevation
X Axis Title(PF)=Main Channel Distance
X Axis Title(XS)=Station
BEGIN DESCRIPTION:
Stream Name- Hogcamp Run
Flood Zone: Zone A
Greenbrier County, WV
County-Wide Study
WVDHSEM-2018-3, Flood Risk Project
HEC-RAS Version: 5.0.7
General Notes:
For the Hydrology regression was used.
END DESCRIPTION:
DSS Export Rating Curves= 0
DSS Export Rating Curve Sorted= 0
DSS Export Volume Flow Curves= 0
DXF Filename=HOGCMPRN.M2.
DXF OffsetX= 0
DXF OffsetY= 0
DXF ScaleX= 1
DXF ScaleY= 10

--- HOGCMPRN.p01 (plan) ---

Plan Title=Floodplain
Program Version=5.07
Short Identifier=Floodplain
Geom File=g01
Flow File=f01
Subcritical Flow
K Sum by GR= 0
Std Step Tol= 0.01
Critical Tol= 0.01
Num of Std Step Trials= 20
Max Error Tol= 0.3
Flow Tol Ratio= 0.001
Split Flow NTrial= 30
Split Flow Tol= 0.02
Split Flow Ratio= 0.02
Log Output Level= 0
Friction Slope Method= 1
Unsteady Friction Slope Method= 2
Unsteady Bridges Friction Slope Method= 1
Parabolic Critical Depth
Global Vel Dist= 0 , 0 , 0
Global Log Level= 0
CheckData=True
Encroach Param=-1 ,0,0, 0
Computation Interval=1MIN
Output Interval=1HOUR
Instantaneous Interval=1HOUR
Mapping Interval=1HOUR
Computation Time Step Use Courant=        0
Computation Time Step Use Time Series=    0
Computation Time Step Count To Double=0
Computation Time Step Max Doubling=0
Computation Time Step Max Halving=0
Computation Time Step Residence Courant=0
Run HTab= 0
Run UNet= 0
Run Sediment= 0
Run PostProcess= 0
Run WQNet= 0
Run RASMapper= 0
UNET Theta= 1
UNET Theta Warmup= 1
UNET ZTol= 0.02
UNET ZSATol= 0.02
UNET MxIter= 20
UNET Max Iter WO Improvement= 0
UNET MaxInSteps= 0
UNET DtIC= 0
UNET DtMin= 0
UNET MaxCRTS= 20
UNET WFStab= 2
UNET SFStab= 1
UNET WFX= 1
UNET SFX= 1
UNET 1D Methodology=Finite Difference
UNET DSS MLevel= 4
UNET Pardiso=0
UNET DZMax Abort= 100
UNET Use Existing IB Tables=-1
UNET Froude Reduction=False
UNET Froude Limit= 0.8
UNET Froude Power= 4
UNET D1 Cores= 0
UNET D2 Coriolis=0
UNET D2 Cores= 0
UNET D2 Theta= 1
UNET D2 Theta Warmup= 1
UNET D2 Z Tol= 0.01
UNET D2 Volume Tol= 0.01
UNET D2 Max Iterations= 20
UNET D2 Equation= 0
UNET D2 RampUpFraction=0.1
UNET D2 TimeSlices= 1
UNET D2 BCVolumeCheck=0
UNET D1D2 MaxIter= 0
UNET D1D2 ZTol=0.01
UNET D1D2 QTol=0.1
UNET D1D2 MinQTol=1
Write IC File= 0
Write IC File at Fixed DateTime=0
Write IC File at Sim End=0
Echo Input=False
Echo Parameters=False
Echo Output=False
Write Detailed= 0
HDF Write Warmup=0
HDF Write Time Slices=0
HDF Flush=0
HDF Face Node Velocities=0
HDF Compression= 1
HDF Chunk Size= 1
HDF Spatial Parts= 1
HDF Use Max Rows=0
HDF Fixed Rows= 1
Calibration Method= 0
Calibration Iterations= 20
Calibration Max Change=0.05
Calibration Tolerance=0.2
Calibration Maximum=1.5
Calibration Minimum=0.5
Calibration Optimization Method= 1
WQ AD Non Conservative
WQ ULTIMATE=-1
WQ Max Comp Step=1HOUR
WQ Output Interval=15MIN
WQ Output Selected Increments= 0
WQ Output face flow=0
WQ Output face velocity=0
WQ Output face area=0
WQ Output face dispersion=0
WQ Output cell volume=0
WQ Output cell surface area=0
WQ Output cell continuity=0
WQ Output cumulative cell continuity=0
WQ Output face conc=0
WQ Output face dconc_dx=0
WQ Output face courant=0
WQ Output face peclet=0
WQ Output face adv mass=0
WQ Output face disp mass=0
WQ Output cell mass=0
WQ Output cell source sink temp=0
WQ Output nsm pathways=0
WQ Output nsm derived pathways=0
WQ Output MaxMinRange=-1
WQ Daily Max Min Mean=-1
WQ Daily Range=0
WQ Daily Time=0
WQ Create Restart=0
WQ Fixed Restart=0
WQ System Summary=0
WQ Write To DSS=0
WQ Use Fixed Temperature=0
Sorting and Armoring Iterations= 10
XS Update Threshold= 0.02
Bed Roughness Predictor= 0
Hydraulics Update Threshold= 0.02
Energy Slope Method= 1
Volume Change Method= 1
Sediment Retention Method= 0
XS Weighting Method= 0
Number of US Weighted Cross Sections= 1
Number of DS Weighted Cross Sections= 1
Upstream XS Weight=0
Main XS Weight=1
Downstream XS Weight=0
Number of DS XS's Weighted with US Boundary= 1
Upstream Boundary Weight= 1
Weight of XSs Associated with US Boundary= 0
Number of US XS's Weighted with DS Boundary= 1
Downstream Boundary Weight= 0.5
Weight of XSs Associated with DS Boundary= 0.5
Percentile Method= 0
Sediment Output Level= 3
Mass or Volume Output= 0
Output Increment Type= 1
Profile and TS Output Increment= 1
XS Output Flag= 0
XS Output Increment= 10
Write Gradation File= 0
Read Gradation Hotstart= 0
Write HDF5 File= 1
Write Binary Output= 1
Write DSS Sediment File= 0
SV Curve= 0
Specific Gage Flag= 0

--- HOGCMPRN.f01 (steady flow) ---

Flow Title=Flow
Program Version=5.07
Number of Profiles= 6
Profile Names=f1p,f10p,f4p,f2p,f02p,f1pplus
River Rch & RM=BEECHRN1,Main            ,6099
     536     283     376     454     750     793
River Rch & RM=BEECHRN1,Main            ,4642
     659     350     465     559     919     975
River Rch & RM=COLDSPRBR,Main            ,7507
     515     271     361     436     721     762
River Rch & RM=COLDSPRBR,Main            ,7028
     574     303     403     486     802     849
River Rch & RM=COLDSPRBR,Main            ,2967
     657     349     463     557     916     972
River Rch & RM=COLDSPRBR,Main            ,1721
     734     392     518     623    1020    1090
River Rch & RM=HOGCMPRN,Main            ,4263
     557     294     391     472     779     824
River Rch & RM=HOGCMPRN,Main            ,3068
     638     338     449     540     889     943
River Rch & RM=JOBKNOBBR2,Main            ,1304
     458     240     321     387     643     678
River Rch & RM=JOBKNOBBR2,Main            ,794
     623     330     439     528     869     922
River Rch & RM=MCMILLCK,Main            ,13233
     571     302     401     483     798     844
River Rch & RM=MCMILLCK,Main            ,9424
     651     346     459     552     907     963
River Rch & RM=MCMILLCK,Main            ,7089
     735     392     519     624    1020    1090
River Rch & RM=MCMILLCK,Main            ,4416
     823     441     583     699    1140    1220
River Rch & RM=MIDDLEBR,Main            ,9120
     499     262     350     422     699     738
River Rch & RM=MIDDLEBR,Main            ,8068
     633     300     399     480     793     839
River Rch & RM=MIDDLEBR,Main            ,6306
     633     336     445     536     882     936
Boundary for River Rch & Prof#=BEECHRN1,Main            , 1
Up Type= 0
Dn Type= 3
Dn Slope=0.035
Boundary for River Rch & Prof#=BEECHRN1,Main            , 2
Up Type= 0
Dn Type= 3
Dn Slope=0.035
Boundary for River Rch & Prof#=BEECHRN1,Main            , 3
Up Type= 0
Dn Type= 3
Dn Slope=0.035
Boundary for River Rch & Prof#=BEECHRN1,Main            , 4
Up Type= 0
Dn Type= 3
Dn Slope=0.035
Boundary for River Rch & Prof#=BEECHRN1,Main            , 5
Up Type= 0
Dn Type= 3
Dn Slope=0.035
Boundary for River Rch & Prof#=BEECHRN1,Main            , 6
Up Type= 0
Dn Type= 3
Dn Slope=0.035
Boundary for River Rch & Prof#=COLDSPRBR,Main            , 1
Up Type= 0
Dn Type= 3
Dn Slope=0.036398
Boundary for River Rch & Prof#=COLDSPRBR,Main            , 2
Up Type= 0
Dn Type= 3
Dn Slope=0.036398
Boundary for River Rch & Prof#=COLDSPRBR,Main            , 3
Up Type= 0
Dn Type= 3
Dn Slope=0.036398
Boundary for River Rch & Prof#=COLDSPRBR,Main            , 4
Up Type= 0
Dn Type= 3
Dn Slope=0.036398
Boundary for River Rch & Prof#=COLDSPRBR,Main            , 5
Up Type= 0
Dn Type= 3
Dn Slope=0.036398
Boundary for River Rch & Prof#=COLDSPRBR,Main            , 6
Up Type= 0
Dn Type= 3
Dn Slope=0.036398
Boundary for River Rch & Prof#=HOGCMPRN,Main            , 1
Up Type= 0
Dn Type= 3
Dn Slope=0.02
Boundary for River Rch & Prof#=HOGCMPRN,Main            , 2
Up Type= 0
Dn Type= 3
Dn Slope=0.02
Boundary for River Rch & Prof#=HOGCMPRN,Main            , 3
Up Type= 0
Dn Type= 3
Dn Slope=0.02
Boundary for River Rch & Prof#=HOGCMPRN,Main            , 4
Up Type= 0
Dn Type= 3
Dn Slope=0.02
Boundary for River Rch & Prof#=HOGCMPRN,Main            , 5
Up Type= 0
Dn Type= 3
Dn Slope=0.02
Boundary for River Rch & Prof#=HOGCMPRN,Main            , 6
Up Type= 0
Dn Type= 3
Dn Slope=0.02
Boundary for River Rch & Prof#=JOBKNOBBR2,Main            , 1
Up Type= 0
Dn Type= 3
Dn Slope=0.043277
Boundary for River Rch & Prof#=JOBKNOBBR2,Main            , 2
Up Type= 0
Dn Type= 3
Dn Slope=0.043277
Boundary for River Rch & Prof#=JOBKNOBBR2,Main            , 3
Up Type= 0
Dn Type= 3
Dn Slope=0.043277
Boundary for River Rch & Prof#=JOBKNOBBR2,Main            , 4
Up Type= 0
Dn Type= 3
Dn Slope=0.043277
Boundary for River Rch & Prof#=JOBKNOBBR2,Main            , 5
Up Type= 0
Dn Type= 3
Dn Slope=0.043277
Boundary for River Rch & Prof#=JOBKNOBBR2,Main            , 6
Up Type= 0
Dn Type= 3
Dn Slope=0.043277
Boundary for River Rch & Prof#=MCMILLCK,Main            , 1
Up Type= 0
Dn Type= 3
Dn Slope=0.03585
Boundary for River Rch & Prof#=MCMILLCK,Main            , 2
Up Type= 0
Dn Type= 3
Dn Slope=0.03585
Boundary for River Rch & Prof#=MCMILLCK,Main            , 3
Up Type= 0
Dn Type= 3
Dn Slope=0.03585
Boundary for River Rch & Prof#=MCMILLCK,Main            , 4
Up Type= 0
Dn Type= 3
Dn Slope=0.03585
Boundary for River Rch & Prof#=MCMILLCK,Main            , 5
Up Type= 0
Dn Type= 3
Dn Slope=0.03585
Boundary for River Rch & Prof#=MCMILLCK,Main            , 6
Up Type= 0
Dn Type= 3
Dn Slope=0.03585
Boundary for River Rch & Prof#=MIDDLEBR,Main            , 1
Up Type= 0
Dn Type= 3
Dn Slope=0.083839
Boundary for River Rch & Prof#=MIDDLEBR,Main            , 2
Up Type= 0
Dn Type= 3
Dn Slope=0.083839
Boundary for River Rch & Prof#=MIDDLEBR,Main            , 3
Up Type= 0
Dn Type= 3
Dn Slope=0.083839
Boundary for River Rch & Prof#=MIDDLEBR,Main            , 4
Up Type= 0
Dn Type= 3
Dn Slope=0.083839
Boundary for River Rch & Prof#=MIDDLEBR,Main            , 5
Up Type= 0
Dn Type= 3
Dn Slope=0.083839
Boundary for River Rch & Prof#=MIDDLEBR,Main            , 6
Up Type= 0
Dn Type= 3
Dn Slope=0.083839
DSS Import GetInterval= 0
DSS Import GetPeak= 0
DSS Import FillOption= 0

--- HOGCMPRN.g01 (geometry) ---

Geom Title=Geometry
Program Version=5.07

River Reach=HOGCMPRN        ,Main
Reach XY= 30
2094682.90809202 408912.450879382094738.19997618408920.595548123
2094797.57518554408976.4983234552094913.89450669409015.387025207
2094974.31138059409086.567657128 2095236.7931391409297.884163633
2095503.47797319409596.6371750382095730.56118044409736.567669466
2095862.50579843409752.1926382182095922.92234427409777.540028468
2096000.35296369409852.1927662942096105.21397445409896.637231216
2096193.40835187410015.7344339642096242.36691535410153.234487042
2096399.96797812410223.2041633732096547.92240661 410408.44263804
2096669.45005068410444.5537862932096754.08702052410415.612243131
2096830.21416485410470.2482887062096861.11666211410649.067812964
2096945.83893362410824.7620153732096974.65842977410858.442722291
2097120.83891168410869.9010327162097170.49169952410887.609330624
 2097191.5943476410916.9878807962097189.83221203410990.699675635
2097217.33215702411075.6995056272097083.58209643411333.199646801
2097076.91544309411501.5329715462097133.42254794  411666.8879558

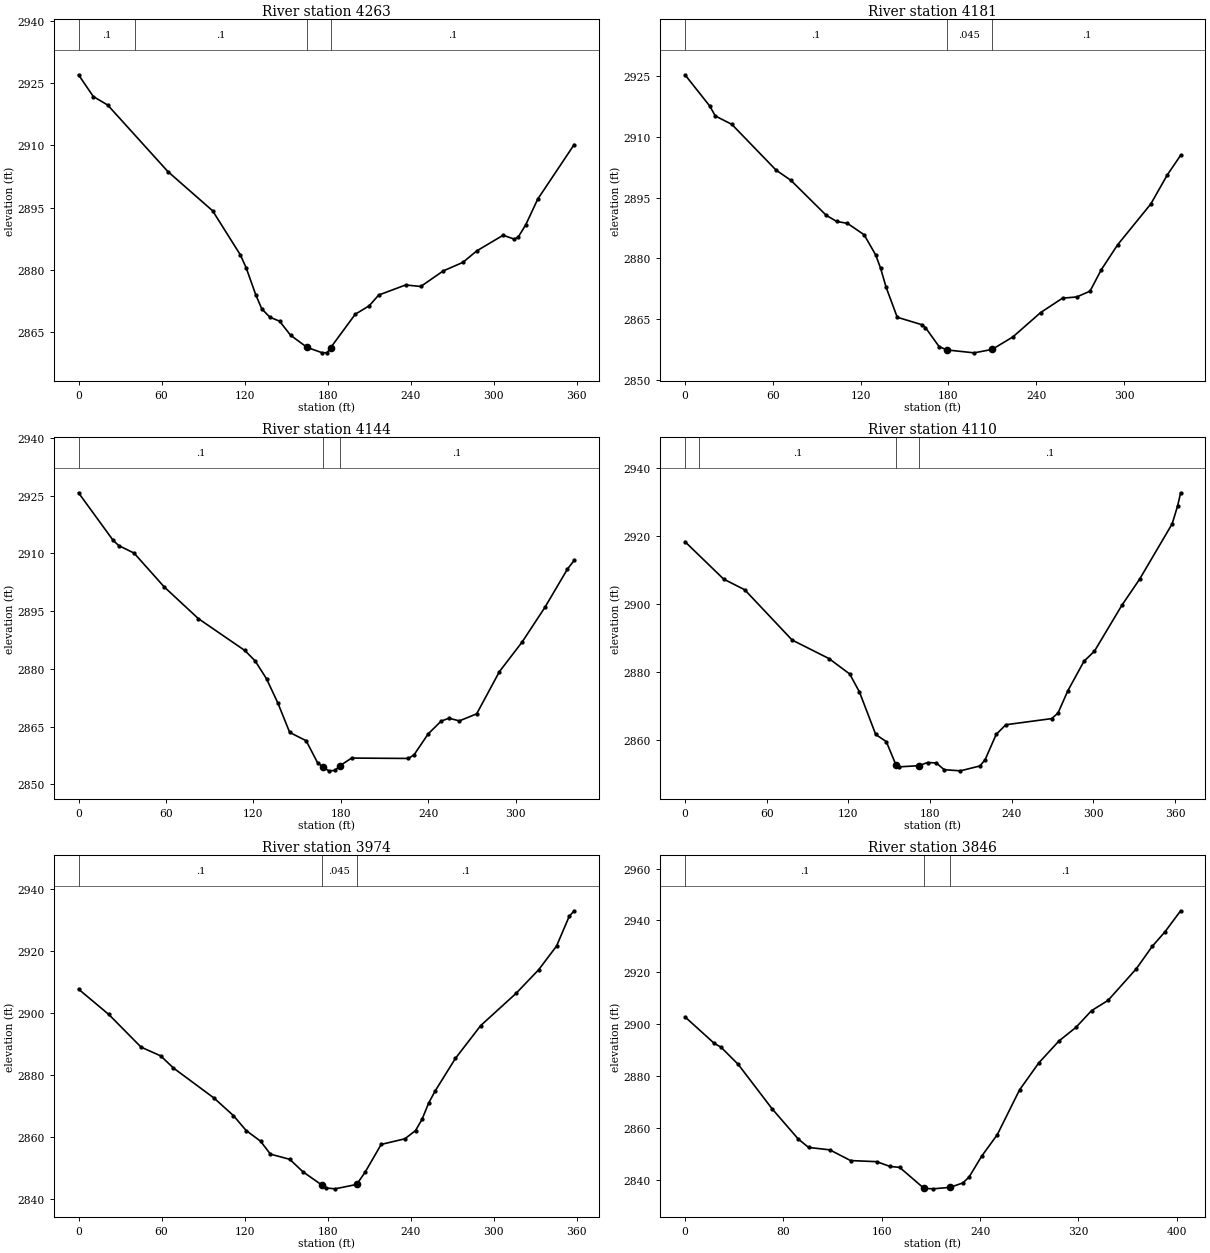
Type RM Length L Ch R = 1 ,4263    ,80.1,82.1,85.6
XS GIS Cut Line= 3
2094638.80844268 409080.974492462094692.80997512408913.846873954
2094736.75706568408736.871506125
#Sta/Elev= 30
       0 2927.02    10.7 2921.78    21.1 2919.73    64.6 2903.71    96.9 2894.27
   116.8 2883.72   121.1 2880.56     128 2874.08   132.4 2870.66   138.3 2868.65
   145.2 2867.72   153.2 2864.31   165.2 2861.38   176.2 2860.09   179.6 2860.14
   182.2 2861.37   199.9 2869.39     210 2871.42   216.8    2874   236.3 2876.43
   247.2 2876.06   263.4  2879.8   277.6 2881.86   287.7 2884.64   306.7  2888.4
   314.8 2887.45   317.6 2887.95     323  2890.9   331.7  2897.1     358 2910.22
#Mann= 4 ,-1 , 0
       0      .1       0   41.05      .1       0   165.2    .045       0
   182.2      .1       0
Bank Sta=165.2,182.2
XS Rating Curve= 0 ,0
Exp/Cntr=0.3,0.1

Type RM Length L Ch R = 1 ,4181    ,36.1,37.2,43.1
XS GIS Cut Line= 2
2094675.32400408409105.2372362842094841.35156566408810.142312341
#Sta/Elev= 30
       0 2925.35      17  2917.6    20.7 2915.18      32 2913.11    62.2 2901.82
    72.4 2899.27    96.5 2890.65   103.6 2889.14     111 2888.66   122.4 2885.84
   130.3 2880.85   133.7 2877.52   137.4 2872.88     145 2865.48   161.6 2863.66
   164.3 2862.92   173.6 2858.23   178.9 2857.41   197.5 2856.69   209.8 2857.53
     224 2860.62   242.9 2866.62   257.9 2870.19   267.6 2870.49   276.7 2871.92
   284.4 2877.22   295.6 2883.39   318.2 2893.44   329.4 2900.57   338.6 2905.47
#Mann= 3 , 0 , 0
       0      .1       0   178.9    .045       0   209.8      .1       0
Bank Sta=178.9,209.8
XS Rating Curve= 0 ,0
Exp/Cntr(USF)=0,0
Exp/Cntr=0.3,0.1

Type RM Length L Ch R = 1 ,4144    ,34.5,33.8,33.6
XS GIS Cut Line= 2
2094697.03078775409116.970632862 2094880.6584442408830.675756353
#Sta/Elev= 30
       0 2925.76    23.7 2913.43    27.6 2912.04    38.1 2910.09    58.8  2901.3
    82.2 2893.07   114.1 2884.78   121.2 2882.07     129 2877.42   136.8 2871.12
   144.9 2863.49   156.2 2861.32     164 2855.63   167.9 2854.42   171.8  2853.5
   175.9 2853.59   179.6 2854.88   187.4 2856.82   226.4 2856.72   230.3  2857.7
   239.9 2863.09   248.8 2866.41   254.2 2867.18   261.3 2866.48   273.2 2868.31
   288.8 2879.28   304.4 2886.98     320 2895.97   335.5 2905.94   340.1 2908.19
#Mann= 3 ,-1 , 0
       0      .1       0   167.9    .045       0   179.6      .1       0
Bank Sta=167.9,179.6
XS Rating Curve= 0 ,0
Exp/Cntr(USF)=0,0
Exp/Cntr=0.3,0.1

Type RM Length L Ch R = 1 ,4110    ,132.2,136.1,137.9
XS GIS Cut Line= 3
 2094731.5165906409130.974392459 2094792.9636462409032.456544876
2094920.05820829408819.516353965
#Sta/Elev= 30
       0 2918.32    28.4 2907.31    43.9 2904.16    78.7 2889.37   105.8 2883.91
     121 2879.38   128.2 2874.05   140.1 2861.58   147.9 2859.46  155.042852.563
   156.9 2852.03   171.8 2852.39   178.2 2853.32   184.6 2853.19   190.4 2851.21
   202.3 2850.87   216.7 2852.31   220.5 2854.17   228.6 2861.59   235.7 2864.44
   269.3 2866.24     274 2867.85   281.3 2874.49   293.1 2883.12   300.8  2886.1
     321 2899.64   333.9 2907.24   357.9 2923.58   361.9 2928.88   364.1 2932.71
#Mann= 4 ,-1 , 0
       0      .1       0   10.07      .1       0  155.04    .045       0
   171.8      .1       0
Bank Sta=155.04,171.8
XS Rating Curve= 0 ,0
Exp/Cntr=0.3,0.1

Type RM Length L Ch R = 1 ,3974    ,129.3,128.4,127.5
XS GIS Cut Line= 3
2094803.39177495409174.7246330382094938.94301301409040.843011051
2095055.47493219408920.557818547
#Sta/Elev= 30
       0 2907.77    21.9 2899.56    45.2    2889    59.3 2886.19    68.6 2882.24
    97.9 2872.53   111.9 2866.86   121.1 2862.03   131.5 2858.58   138.6 2854.41
   152.6 2852.72     162 2848.73     176 2844.33   179.1 2843.45   185.3 2843.18
   200.9  2844.6     207 2848.56   218.6 2857.54   235.7 2859.36   243.4 2862.01
   248.1 2865.64   252.8 2870.82   257.5 2874.77   272.2 2885.34   290.5 2895.98
     316 2906.38   332.3    2914   345.3 2921.71   354.4 2931.28     358  2933.1
#Mann= 3 , 0 , 0
       0      .1       0     176    .045       0   200.9      .1       0
Bank Sta=176,200.9
XS Rating Curve= 0 ,0
Exp/Cntr=0.3,0.1

Type RM Length L Ch R = 1 ,3846    ,166.2,167,167
XS GIS Cut Line= 2
2094897.14158744409289.3077372162095154.43339568408978.891363293
#Sta/Elev= 30
       0 2902.81    23.9 2892.55    29.3  2891.1    43.3 2884.48    70.8 2867.38
    92.2 2855.65   100.6 2852.43   117.8  2851.5   134.7 2847.37     156 2846.94
   166.8 2845.09   174.6 2844.75   194.4 2836.66   201.7 2836.46   215.7 2837.03
   215.7 2837.04     226 2838.73   231.1 2840.99   241.3 2849.03     254 2857.31
   272.2 2874.66   287.9 2885.09   304.2  2893.5     318 2898.73   330.7 2905.19
   344.2 2909.18   367.1 2921.34   380.2 2930.07   390.4 2935.57   403.2 2943.73
#Mann= 3 , 0 , 0
       0      .1       0   194.4    .045       0   215.7      .1       0
Bank Sta=194.4,215.7
XS Rating Curve= 0 ,0
Exp/Cntr=0.3,0.1

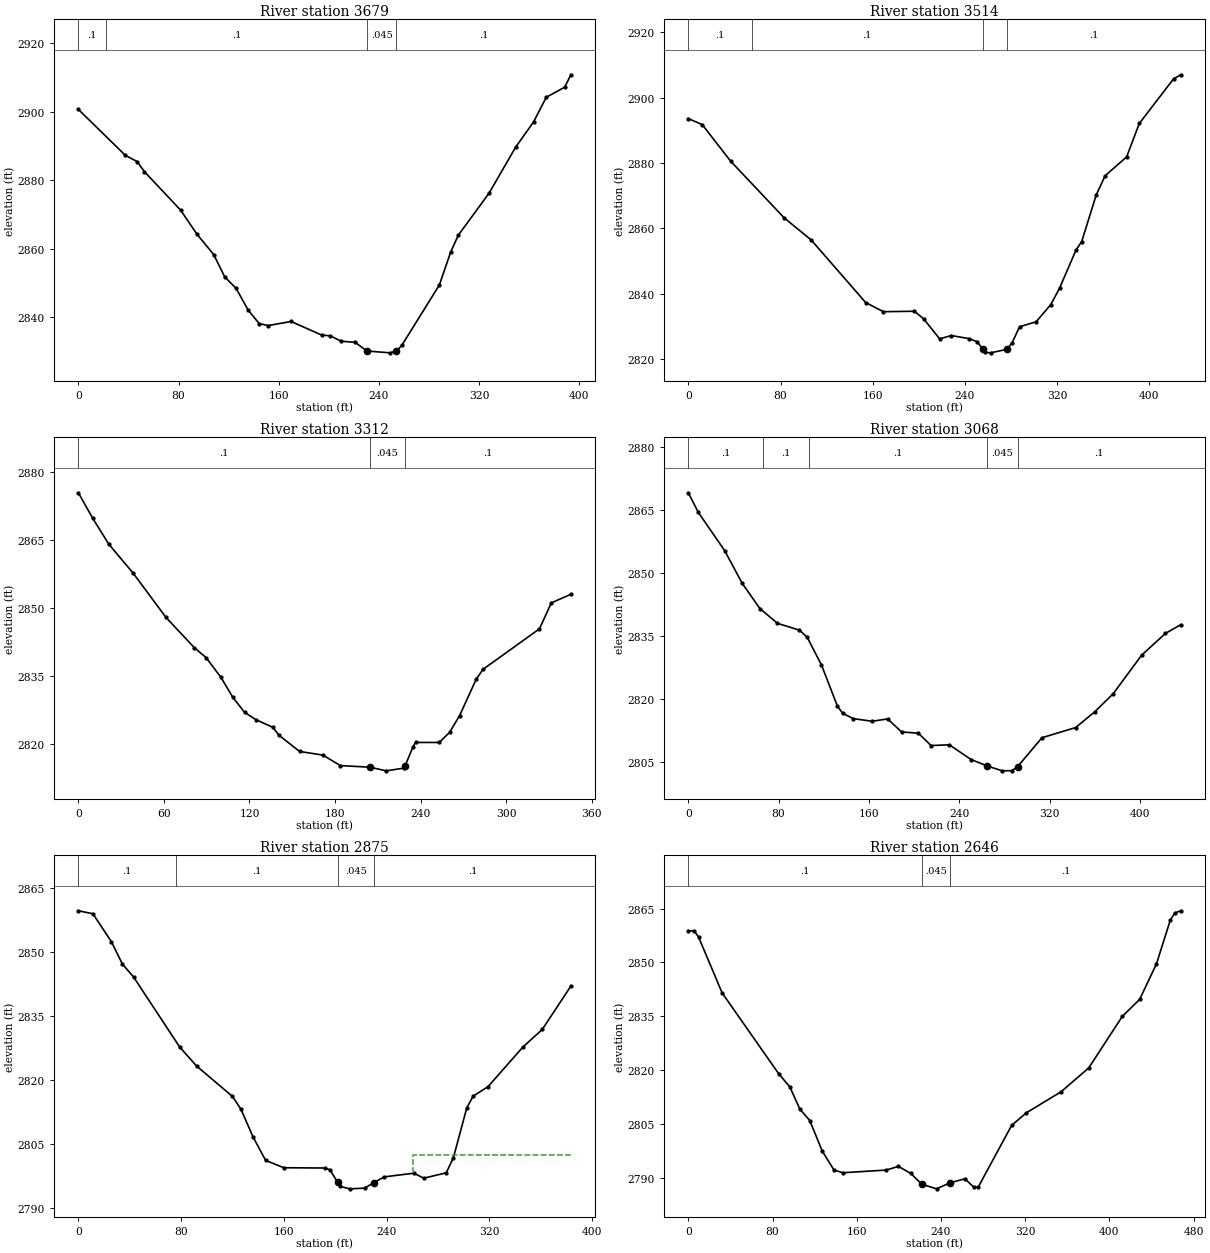
Type RM Length L Ch R = 1 ,3679    ,163.7,164.7,166.2
XS GIS Cut Line= 3
2094996.10005093409413.2661507132095159.39893693409233.200894043
2095257.55818945409119.516082048
#Sta/Elev= 30
       0  2900.7    37.6 2887.27    46.9 2885.49    52.7 2882.55    81.7 2871.28
    94.8 2864.22   108.1 2858.33   116.9 2851.79   125.9 2848.49   135.7 2842.06
   144.4 2838.18   151.4 2837.59   169.9 2838.78   194.3 2834.82   201.1  2834.6
   209.9 2833.03   221.1 2832.69   230.4 2830.17     249 2829.63     254 2830.13
   258.3 2831.81   288.3 2849.44   297.3 2859.02   303.4 2863.96   328.1 2876.31
   349.3 2889.72   363.6 2897.09   373.7 2904.26   388.4 2907.19   393.3 2910.81
#Mann= 4 ,-1 , 0
       0      .1       0   22.06      .1       0   230.4    .045       0
     254      .1       0
Bank Sta=230.4,254
XS Rating Curve= 0 ,0
Exp/Cntr=0.3,0.1

Type RM Length L Ch R = 1 ,3514    ,201.3,202.1,203
XS GIS Cut Line= 2
2095081.51654679409520.5579308722095401.30823001409237.224508047
#Sta/Elev= 30
       0 2893.58    12.1 2891.73    36.8 2880.51    83.3 2863.14   106.6 2856.42
   153.9 2837.25   169.3 2834.45   196.2 2834.58   204.2 2832.25   218.1 2826.12
   228.1 2827.15   243.7  2826.2   250.7 2825.22   255.3  2823.1   257.6 2822.01
   262.3 2821.85   276.2  2822.9   280.9 2824.89   287.4 2829.83   301.8 2831.37
   314.5 2836.61   322.1 2841.64   336.4 2853.33   341.3 2855.91     354 2870.27
   361.7  2876.1   380.3 2881.84   391.3 2892.08     421 2905.73   427.3 2906.99
#Mann= 4 ,-1 , 0
       0      .1       0    55.2      .1       0   255.3    .045       0
   276.2      .1       0
Bank Sta=255.3,276.2
XS Rating Curve= 0 ,0
Exp/Cntr=0.3,0.1

Type RM Length L Ch R = 1 ,3312    ,247.5,244.2,238.8
XS GIS Cut Line= 2
2095240.89155611409628.891375631 2095514.8499977409418.474473625
#Sta/Elev= 30
       0 2875.33    10.1 2869.71    21.4    2864    38.4 2857.66    61.5 2847.89
    81.4 2841.23    89.6 2839.06     100 2834.72   108.3 2830.34   116.6 2827.02
   124.5 2825.41   136.4 2823.73   140.7 2821.98   155.1 2818.42   171.5 2817.61
   183.8  2815.3   204.3 2814.96     216 2814.15   228.3 2814.75  229.112815.227
   234.7 2819.43   236.5  2820.4   253.1 2820.39   260.4 2822.64   267.4 2826.31
   279.1 2834.36   283.8 2836.48   323.4  2845.4   331.7 2851.11   345.4 2852.99
#Mann= 3 ,-1 , 0
       0      .1       0   204.3    .045       0  229.11      .1       0
Bank Sta=204.3,229.11
XS Rating Curve= 0 ,0
Exp/Cntr=0.3,0.1

Type RM Length L Ch R = 1 ,3068    ,193.2,193.3,192.8
XS GIS Cut Line= 3
2095447.14179978409882.0161974582095500.44451469409798.791954458
2095683.59998828409515.349607959
#Sta/Elev= 30
       0 2869.06     8.9 2864.38    32.2 2855.28    47.8 2847.46    63.4 2841.47
      79 2837.95    98.5 2836.31   105.3 2834.64     118 2828.01     132 2818.28
   136.7 2816.51   146.2 2815.23   162.8 2814.61   176.6 2815.16   188.9 2812.07
   203.9 2811.75     215 2808.82   231.3 2808.99   250.6 2805.47   264.9 2803.95
   278.2 2802.79   286.6 2802.83  291.672803.772   313.3 2810.68   343.2 2813.11
   360.2 2816.89   376.4 2821.16   401.5 2830.32   422.7 2835.55   436.3 2837.62
#Mann= 5 ,-1 , 0
       0      .1       0   66.57      .1       0   106.6      .1       0
   264.9    .045       0  291.67      .1       0
Bank Sta=264.9,291.67
XS Rating Curve= 0 ,0
Exp/Cntr=0.3,0.1

Type RM Length L Ch R = 1 ,2875    ,226,228.8,228.6
XS GIS Cut Line= 2
2095651.30838618409926.8077745442095851.30831426409599.724439204
#Sta/Elev= 30
       0  2859.6    11.3 2858.91    25.7 2852.38    34.3 2847.13      43  2844.1
    78.8 2827.75      92 2823.28     120 2816.15   126.5  2813.2     136 2806.68
   145.8 2801.18   159.9 2799.47     192  2799.4   195.8    2799   201.8  2796.1
   203.5 2795.13   211.2 2794.53   222.8 2794.69  230.212796.006   238.1 2797.33
   261.2 2798.19   268.9 2797.02   286.4 2798.28     292 2801.86   302.4 2813.49
   307.4 2816.24   318.9 2818.43     346 2827.69   361.2 2831.85   383.4 2841.97
#Mann= 4 ,-1 , 0
       0      .1       0   76.07      .1       0   201.8    .045       0
  230.21      .1       0
#XS Ineff= 2 , 0
                          260.33         2802.49
Permanent Ineff=
       F       F
Bank Sta=201.8,230.21
XS Rating Curve= 0 ,0
Exp/Cntr=0.3,0.1

Type RM Length L Ch R = 1 ,2646    ,254.1,256.5,257.3
XS GIS Cut Line= 2
2095822.14170593410010.1412692962096108.60012251409640.349686041
#Sta/Elev= 30
       0 2858.76     5.5 2858.78     9.7  2857.1    32.2 2841.48    85.8 2819.04
    96.5 2815.32     106 2809.15   115.4    2806   127.1 2797.56   138.3 2792.25
   146.6 2791.46   187.9  2792.2   199.6 2793.23   211.3 2791.27   221.72788.288
   235.8 2786.98   248.7 2788.67   262.7 2789.77   271.1 2787.47   275.3 2787.42
   307.1 2804.62   320.9 2808.11   354.1    2814   380.4 2820.65   412.2 2834.96
   428.8 2839.74   444.7 2849.61   457.9 2861.82     462 2863.75   467.8 2864.37
#Mann= 3 ,-1 , 0
       0      .1       0   221.7    .045       0   248.7      .1       0
Bank Sta=221.7,248.7
XS Rating Curve= 0 ,0
Exp/Cntr=0.3,0.1

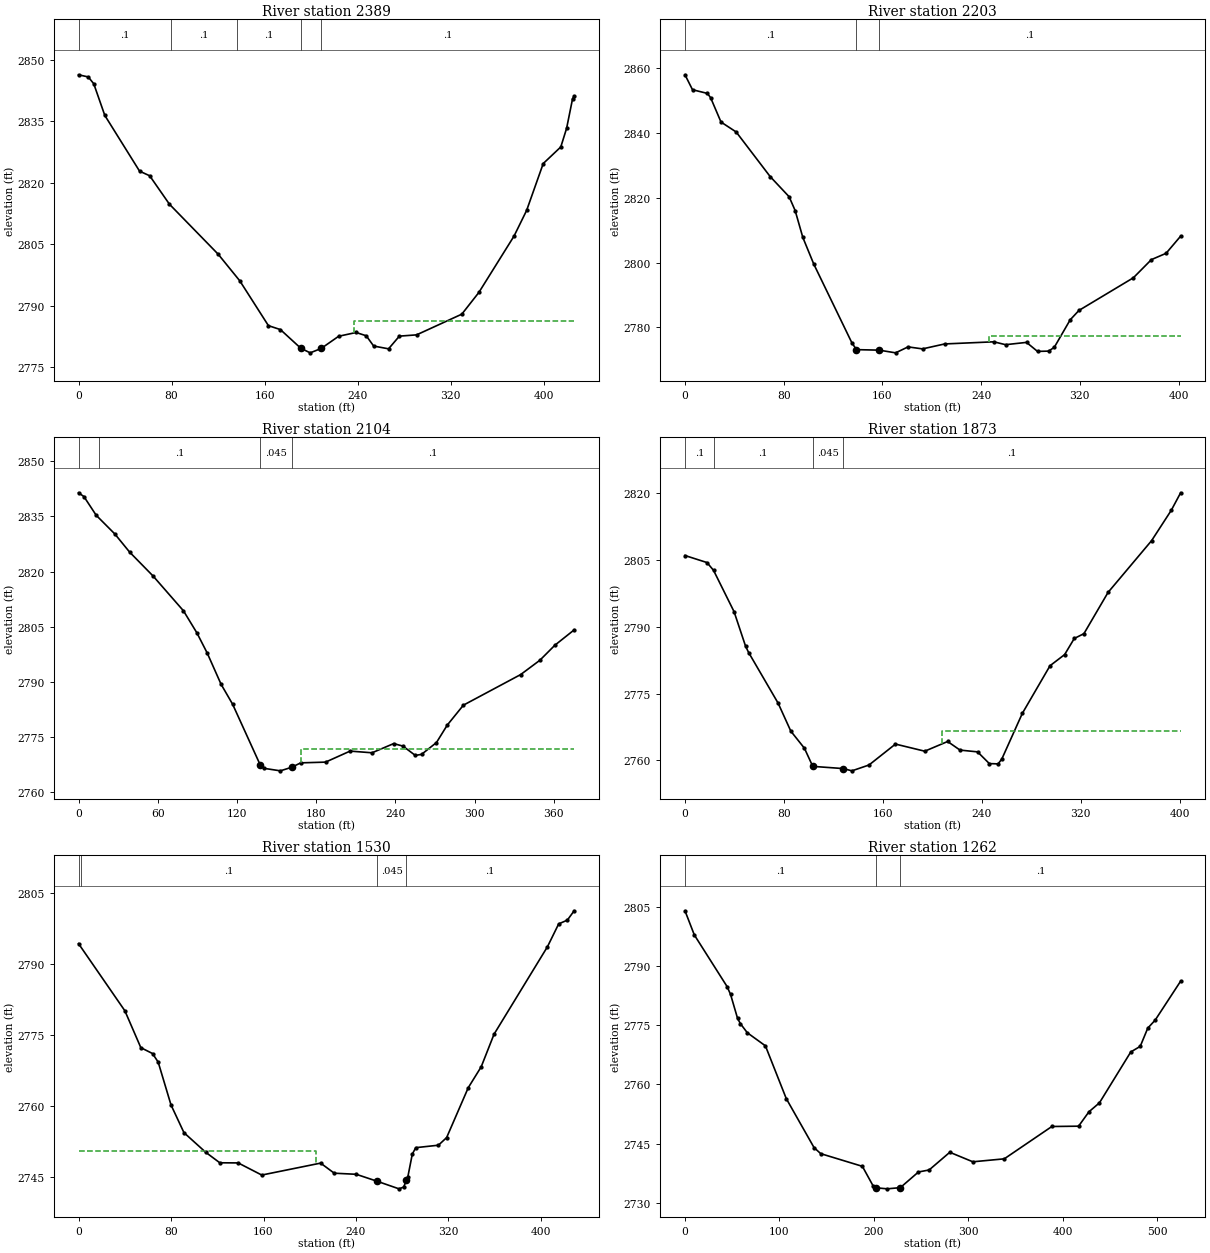
Type RM Length L Ch R = 1 ,2389    ,186.1,185.9,185.5
XS GIS Cut Line= 2
2096005.47500068410109.0994047082096328.39167768409830.974632874
#Sta/Elev= 30
       0 2846.36     8.4 2845.83    13.1 2844.17    22.6 2836.44    52.5 2822.82
    61.2 2821.69    78.2 2814.74   120.1 2802.53   138.7 2796.02   163.3 2785.08
   173.6 2784.12   191.1 2779.57   199.2 2778.44   208.6  2779.5   223.7 2782.49
   238.7 2783.41   247.4 2782.61   253.8  2780.1   266.6 2779.42   275.9 2782.52
   290.7 2782.83   329.6 2787.89   344.3 2793.21   374.5 2806.96   385.3 2813.21
   399.6 2824.68   414.7 2828.73   419.7 2833.28   424.8 2840.47   426.2 2841.16
#Mann= 5 ,-1 , 0
       0      .1       0   79.78      .1       0  136.16      .1       0
   191.1    .045       0   208.6      .1       0
#XS Ineff= 2 , 0
                          237.13         2786.18
Permanent Ineff=
       F       F
Bank Sta=191.1,208.6
XS Rating Curve= 0 ,0
Exp/Cntr=0.3,0.1

Type RM Length L Ch R = 1 ,2203    ,100.5,99.4,98.2
XS GIS Cut Line= 2
2096122.01000937410242.7992320852096420.06916138409973.552464764
#Sta/Elev= 30
       0 2858.04     6.1 2853.42    18.2 2852.28    20.8 2850.94    29.2 2843.43
    41.5 2840.36      69  2826.6    84.4 2820.35    89.3 2816.06    95.5 2807.78
   104.4 2799.51   135.3 2775.17     139 2773.09   157.4 2772.93   170.7  2772.1
   180.8 2773.94   192.5 2773.32   210.5 2774.85   250.3 2775.51   259.8 2774.62
   276.8 2775.33   285.7 2772.55   294.7 2772.63   299.3 2773.81   312.2 2782.31
   319.3 2785.21   363.4  2795.3     378 2800.91   389.9 2802.86   401.7 2808.16
#Mann= 3 , 0 , 0
       0      .1       0     139    .045       0   157.4      .1       0
#XS Ineff= 2 , 0
                          246.19         2777.36
Permanent Ineff=
       F       F
Bank Sta=139,157.4
XS Rating Curve= 0 ,0
Exp/Cntr(USF)=0,0
Exp/Cntr=0.3,0.1

Type RM Length L Ch R = 1 ,2104    ,232.6,231.5,230.8
XS GIS Cut Line= 2
2096231.51654336410305.9746671322096454.43342036410003.891281798
#Sta/Elev= 30
       0 2841.44     4.1 2840.41    13.4 2835.32    27.5 2830.24    38.7 2825.31
    56.5 2818.79    79.5 2809.33    89.7 2803.31    97.5 2797.83     108 2789.34
   116.7 2783.94   137.8 2767.28   140.7 2766.48   152.9 2765.81   161.5 2766.79
   168.3 2767.98   187.1 2768.18   205.7 2771.18   222.3 2770.72   238.7 2773.22
   245.7 2772.54   255.1    2770   259.8 2770.29   271.1  2773.5   279.3 2778.26
   291.5 2783.67   334.9    2792   349.4 2795.88   360.8 2799.98   375.4 2804.15
#Mann= 4 ,-1 , 0
       0      .1       0   15.69      .1       0   137.8    .045       0
   161.5      .1       0
#XS Ineff= 2 , 0
                          168.42         2771.81
Permanent Ineff=
       F       F
Bank Sta=137.8,161.5
XS Rating Curve= 0 ,0
Exp/Cntr=0.3,0.1

Type RM Length L Ch R = 1 ,1873    ,341.5,342.6,341.5
XS GIS Cut Line= 2
2096425.26681203410434.0994108772096642.97503802410097.641094297
#Sta/Elev= 30
       0 2806.01    17.8 2804.43    23.1 2802.68    39.7 2793.39      49 2785.64
    51.5 2784.21    75.3 2772.86    85.6 2766.56    96.6 2762.72  103.322758.655
   127.9 2758.16     135 2757.65   148.8 2758.96   170.2 2763.66   193.9 2762.06
   212.4 2764.24   222.4 2762.31   236.6 2761.91   246.1 2759.28   253.2 2759.21
   256.2  2760.3   272.8 2770.56   295.2 2781.26     307 2783.76   314.8 2787.38
   322.6 2788.46   342.1 2797.72   377.3 2809.34   393.2 2816.15   400.8  2820.1
#Mann= 4 ,-1 , 0
       0      .1       0   23.32      .1       0  103.32    .045       0
   127.9      .1       0
#XS Ineff= 2 , 0
                           207.7         2766.58
Permanent Ineff=
       F       F
Bank Sta=103.32,127.9
XS Rating Curve= 0 ,0
Exp/Cntr=0.3,0.1

Type RM Length L Ch R = 1 ,1530    ,257.6,267.8,273.5
XS GIS Cut Line= 3
2096648.18336093410664.3079399622096678.76171187410617.851011872
 2096855.4749411410289.308033794
#Sta/Elev= 30
       0 2794.31    40.1 2780.13    53.9 2772.35      64 2771.11    68.9 2769.31
      80 2760.26    91.2 2754.41     110 2750.27   122.2 2748.05   138.1 2748.02
   158.5 2745.46   209.4 2747.98   221.2 2745.85   240.2 2745.62  257.832744.189
   277.2 2742.55   281.2 2742.92   283.6 2744.32   284.9 2745.15   288.7 2749.88
   291.7 2751.24   311.3 2751.76   318.4 2753.37   337.1  2763.9   348.3 2768.31
   359.4 2775.19   405.6 2793.65   415.3 2798.47   422.8 2799.27   428.7 2801.24
#Mann= 4 ,-1 , 0
       0      .1       0    1.96      .1       0  257.83    .045       0
   283.6      .1       0
#XS Ineff= 2 , 0
          205.15 2750.46
Permanent Ineff=
       F       F
Bank Sta=257.83,283.6
XS Rating Curve= 0 ,0
Exp/Cntr=0.3,0.1

Type RM Length L Ch R = 1 ,1262    ,179.2,174.2,169.7
XS GIS Cut Line= 2
2096674.83410059 410766.829515662097142.16141301410527.646245524
#Sta/Elev= 30
       0 2803.95     9.9 2797.83    44.6 2784.75    48.3 2782.75    55.7 2776.69
    58.7 2775.36      66 2773.06    85.2 2769.74   107.3 2756.37   136.7 2743.97
   143.8 2742.43   187.9 2739.22   199.4 2734.21   202.62733.782   214.2 2733.52
   228.12733.826   247.3 2737.79   258.6  2738.3   280.5 2742.78   304.9 2740.37
   338.2 2741.12   388.6 2749.31   416.9 2749.39   427.9 2753.04     439  2755.3
   472.2 2768.19   482.2 2769.61   490.2 2774.23     498 2776.24     525 2786.12
#Mann= 3 ,-1 , 0
       0      .1       0   202.6    .045       0   228.1      .1       0
Bank Sta=202.6,228.1
XS Rating Curve= 0 ,0
Exp/Cntr(USF)=0,0
Exp/Cntr=0.3,0.1

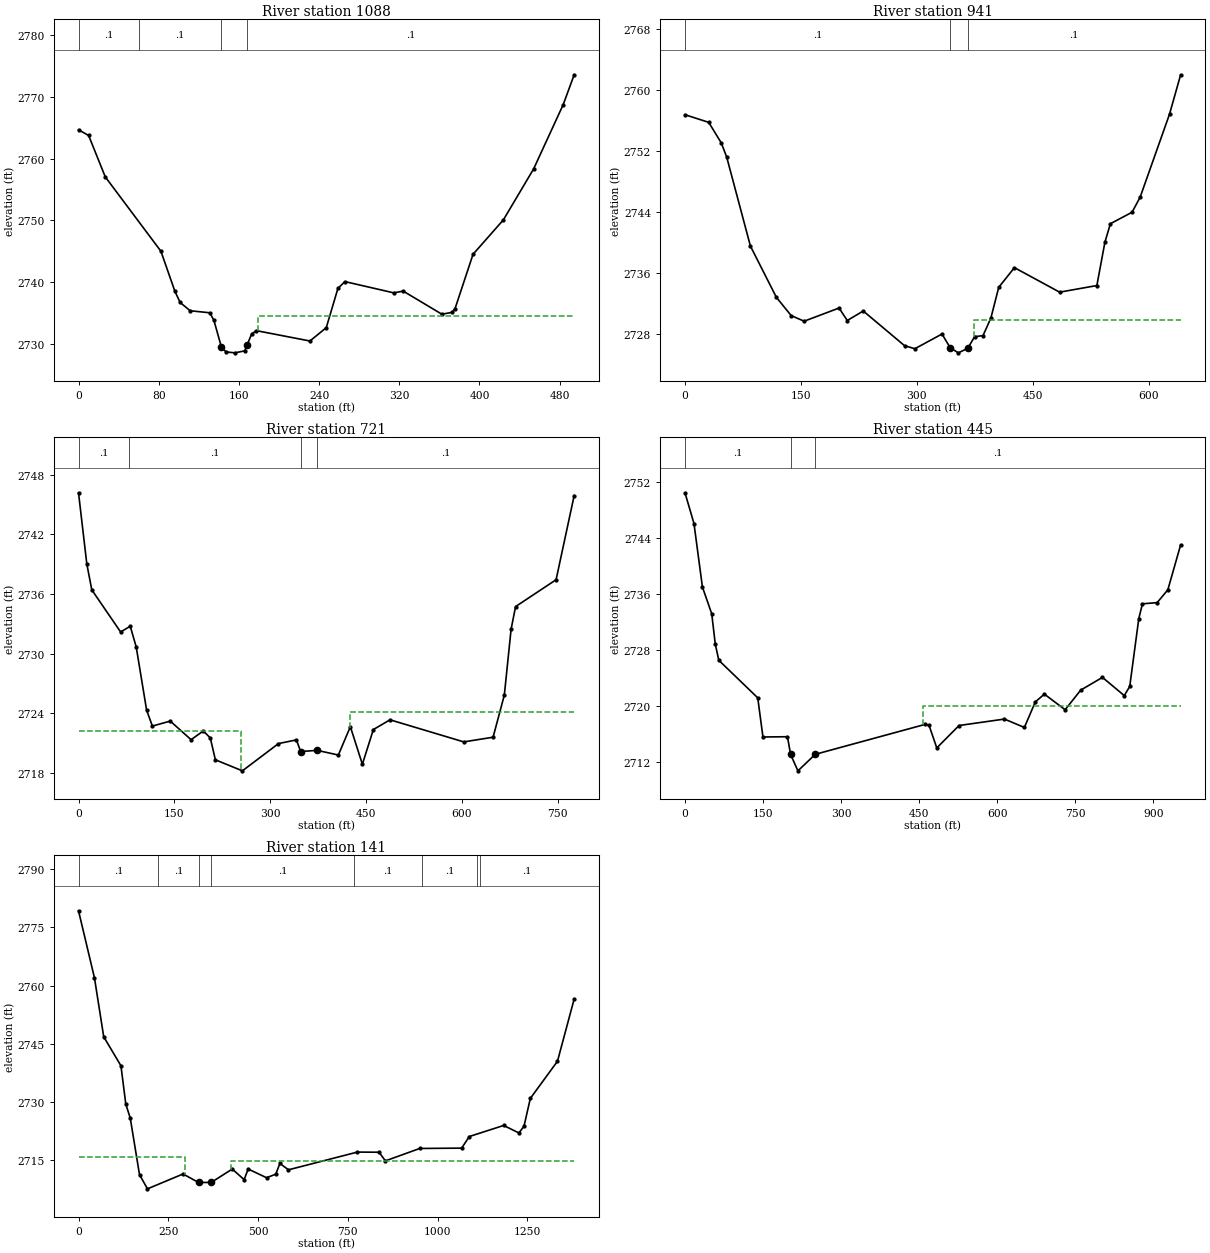
Type RM Length L Ch R = 1 ,1088    ,151,147.1,142
XS GIS Cut Line= 3
2096835.68331403410935.1410597122096882.30034676410893.731693715
2097167.97497228410569.516134799
#Sta/Elev= 30
       0 2764.69    10.1 2763.77    26.7 2757.05    82.2 2744.99    96.1 2738.51
   101.4 2736.67   111.4 2735.33     131    2735   135.1 2733.76   142.6 2729.42
   147.2 2728.65     156  2728.5   165.8 2728.82   168.2 2729.78   172.8 2731.58
   177.5  2732.1   230.9 2730.42   247.2 2732.59   258.8 2738.96   265.8 2740.06
   314.6 2738.23   323.9 2738.52   362.5 2734.77   372.7 2735.07   375.6 2735.65
   393.6 2744.49   423.9 2750.08   454.1 2758.36   483.6 2768.79   494.5 2773.62
#Mann= 4 ,-1 , 0
       0      .1       0   60.01      .1       0   142.6    .045       0
   168.2      .1       0
#XS Ineff= 2 , 0
                           179.4         2734.55
Permanent Ineff=
       F       F
Bank Sta=142.6,168.2
XS Rating Curve= 0 ,0
Exp/Cntr=0.3,0.1

Type RM Length L Ch R = 1 ,941     ,212.7,219.5,222.7
XS GIS Cut Line= 3
2096909.11104723411180.1872696892097026.86281099410990.067234453
2097176.50567744410600.014517001
#Sta/Elev= 30
       0 2756.73    30.7 2755.73    46.9 2753.05      54 2751.17    84.7 2739.49
   118.3 2732.77   137.4 2730.38   154.2 2729.64   199.4 2731.37     210 2729.73
   230.7 2730.98   284.1 2726.43   297.5 2726.03   332.6 2727.96   343.1 2726.17
   353.7 2725.49   365.92726.076   374.8 2727.61   385.7 2727.75   395.9 2730.07
     406 2734.08   426.3 2736.67   484.8 2733.45     533 2734.32   543.4    2740
   550.5 2742.43   578.6 2743.94   589.1 2745.94     627  2756.8   641.4 2761.97
#Mann= 3 ,-1 , 0
       0      .1       0   343.1    .045       0   365.9      .1       0
#XS Ineff= 2 , 0
                          374.22         2729.83
Permanent Ineff=
       F       F
Bank Sta=343.1,365.9
XS Rating Curve= 0 ,0
Exp/Cntr(USF)=0,0
Exp/Cntr=0.3,0.1

Type RM Length L Ch R = 1 ,721     ,252.2,275.8,275.3
XS GIS Cut Line= 4
2096922.14180252411244.5160971282096981.61740535411216.205786288
2097348.23215768410841.0080458822097415.89179927410668.474598289
#Sta/Elev= 30
       0 2746.18      13 2739.02    20.8 2736.42    65.9 2732.19      81 2732.76
    90.3 2730.69   106.6 2724.33   115.6 2722.73   143.6 2723.23   176.2 2721.36
   195.4 2722.24   206.3 2721.53   214.2 2719.34   256.5 2718.23     313 2720.97
     341 2721.34   347.8 2720.17   373.4 2720.29   406.7 2719.82   425.5 2722.67
   444.3 2718.89   461.5 2722.38   487.6 2723.36     603 2721.14   648.9 2721.61
   666.5 2725.85   677.1 2732.47   684.1 2734.74   747.5 2737.44   775.8  2745.9
#Mann= 4 ,-1 , 0
       0      .1       0   79.56      .1       0   347.8    .045       0
   373.4      .1       0
#XS Ineff= 2 , 0
          254.89 2722.24  424.67          2724.1
Permanent Ineff=
       F       F
Bank Sta=347.8,373.4
XS Rating Curve= 0 ,0
Exp/Cntr=0.3,0.1

Type RM Length L Ch R = 1 ,445     ,316.5,304.9,288.1
XS GIS Cut Line= 5
2096907.88446636411257.4618646562097030.54255361411223.117600226
 2097204.7170375411261.1416072732097296.71060294411093.100027742
2097451.25979287410665.023303243
#Sta/Elev= 30
       0 2750.41    17.3 2746.02    33.5 2736.96    51.4 2733.14    58.2 2728.82
      65  2726.5   139.8 2721.14   149.8 2715.55   196.9 2715.59  202.91 2713.06
     217 2710.72   250.4 2713.08   461.4 2717.35   468.8 2717.24   483.8 2713.99
   526.6 2717.19   613.8 2718.11   652.1 2716.91   673.1 2720.56   690.5 2721.67
   730.4 2719.44   760.3 2722.24   802.1 2724.06     844 2721.46   854.5 2722.76
   871.9 2732.45   878.9 2734.56   907.2 2734.73   927.7 2736.56   952.3 2742.97
#Mann= 3 , 0 , 0
       0      .1       0  202.91    .045       0   250.4      .1       0
#XS Ineff= 2 , 0
                          457.04         2719.93
Permanent Ineff=
       F       F
Bank Sta=202.91,250.4
XS Rating Curve= 0 ,0
Exp/Cntr(USF)=0,0
Exp/Cntr=0.3,0.1

Type RM Length L Ch R = 1 ,141     ,143.51,140.55,137.83
XS GIS Cut Line= 6
2096776.85239494411706.6601859632097035.56710061 411573.01150313
2097112.81399336411515.3830094642097284.47309884411173.290845871
2097499.04681668410644.826023549 2097511.3082751410606.815928966
#Sta/Elev= 30
       0 2779.28    44.4 2761.99    70.2 2746.79   118.2 2739.31   131.7 2729.43
   144.1 2725.84   169.9 2711.23   192.1 2707.58   291.2 2711.41  334.32 2709.22
   369.6 2709.23   428.2 2712.68   461.4 2709.95   472.5 2712.69   523.7 2710.45
   549.5 2711.35   560.8 2714.12   584.9 2712.49   776.9 2717.06   837.1 2717.02
   854.8 2714.79   950.4 2717.99  1067.2 2718.08  1088.5 2721.07  1184.1 2723.92
  1226.6    2722  1240.8  2723.7  1258.5  2730.9  1334.1 2740.48  1380.6 2756.53
#Mann= 8 ,-1 , 0
       0      .1       0  222.19      .1       0  334.32    .045       0
   369.6      .1       0  767.69      .1       0  957.33      .1       0
 1109.46      .1       0 1119.25      .1       0
#XS Ineff= 2 , 0
          297.37 2715.89  424.34          2714.7
Permanent Ineff=
       F       F
Bank Sta=334.32,369.6
XS Rating Curve= 0 ,0
Exp/Cntr=0.3,0.1
LCMann Table=0

Chan Stop Cuts=-1
Use User Specified Reach Order=0
Composite Channel Slope=5